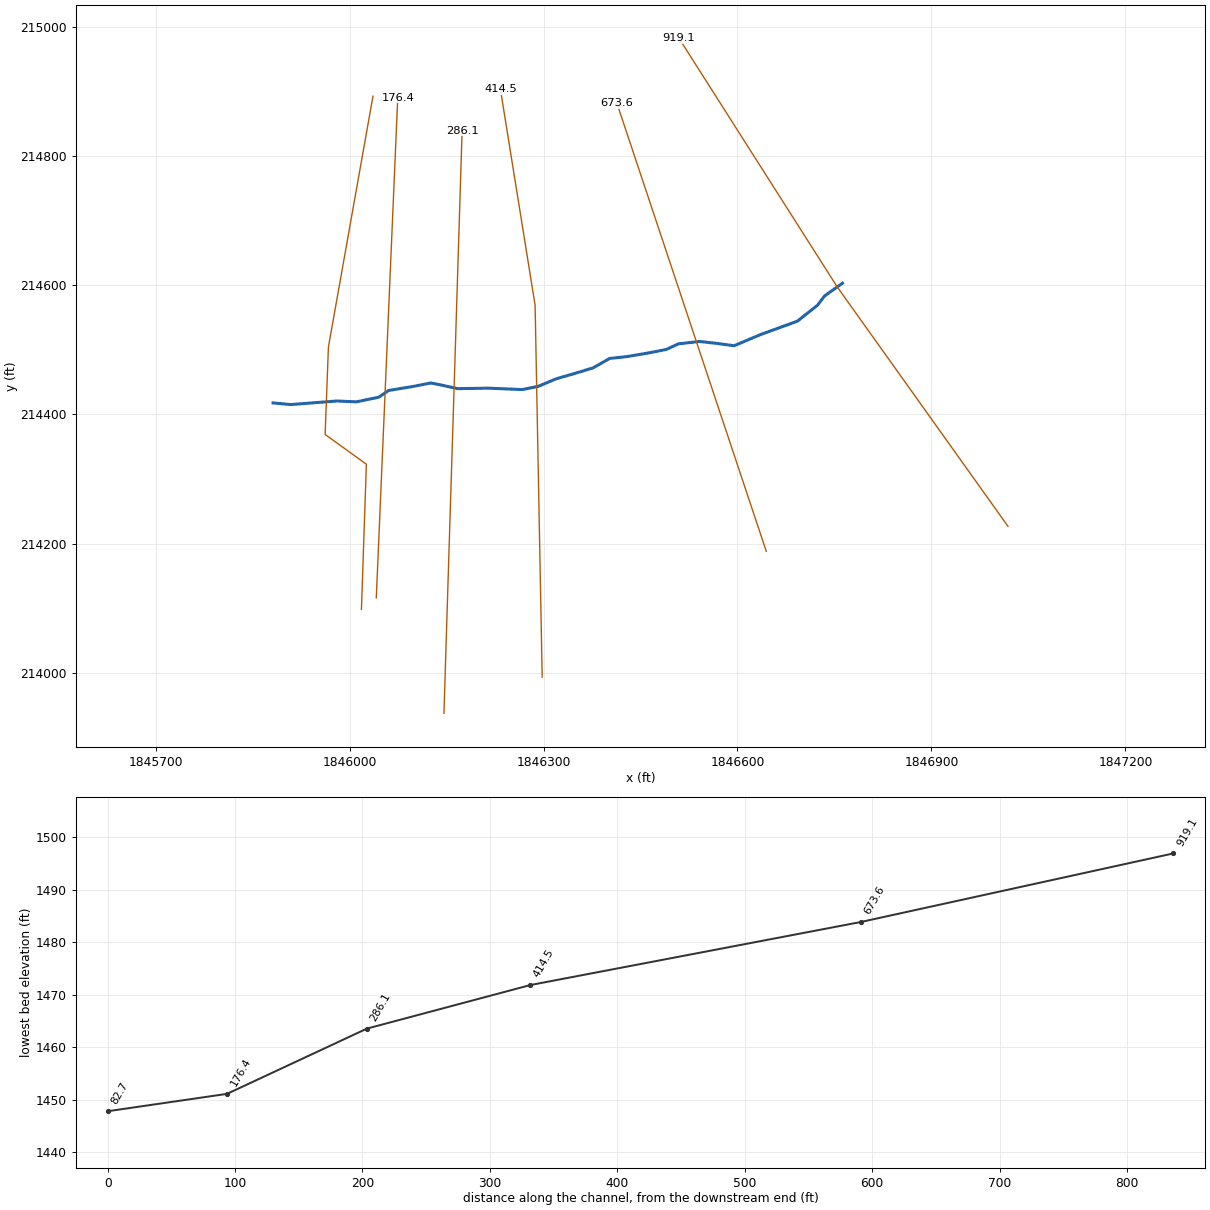
--- NP1576.prj (project) ---

Proj Title=NP1576
Current Plan=p01
Default Exp/Contr=0,0
English Units
Geom File=g01
Flow File=f01
Plan File=p01
BEGIN DESCRIPTION:
END DESCRIPTION:
DSS Export Rating Curves= 0
DSS Export Rating Curve Sorted= 0
DSS Export Volume Flow Curves= 0
DXF OffsetX= 0
DXF OffsetY= 0
DXF ScaleX= 0
DXF ScaleY= 0

--- NP1576.p01 (plan) ---

Plan Title=Floodplain
Program Version=4.00
Geom File=g01
Flow File=f01
K Sum by GR=0
Std Step Tol=0.01
Critical Tol=0.01
Num of Std Step Trials=20
Max Error Tol=0.3
Flow Tol Ratio=0.001
Split Flow NTrial=30
Split Flow Tol=0.02
Split Flow Ratio=0.02
Log Output Level=0
Friction Slope Method=1
Unsteady Friction Slope Method=2
Unsteady Bridges Friction Slope Method=1
Global Log Level=0
CheckData=False
Run HTab=0
Run UNet=0
Run PostProcess=0
UNET Theta=0
UNET Theta Warmup=0
UNET ZTol=0
UNET ZSATol=0
UNET MxIter=0
UNET MaxInSteps=0
UNET DtIC=0
UNET DtMin=0
UNET MaxCRTS=0
UNET WFStab=0
UNET SFStab=0
UNET WFX=0
UNET SFX=0
UNET DSS MLevel=0
UNET DZMax Abort=0
UNET Convert EG Bridges=0
UNET Use Existing IB Tables=0
UNET Froude Limit=0
UNET Froude Power=0
Write IC File=0
Echo Input=False
Echo Output=False
Write Detailed=0

--- NP1576.f01 (steady flow) ---

Flow Title=NFF Regression Equation
Program Version=4.00
Number of Profiles=1
Profile Names=P100yr
River Rch & RM=NP1576,Main      ,919.1
563.6096
River Rch & RM=NP1576,Main      ,286.1
572.3809
Boundary for River Rch & Prof#=NP1576,Main      ,1
Up Type=0
Dn Type=3
Dn Slope=0.071137

--- NP1576.g01 (geometry) ---

Geom Title=USGS 10m DEM
Program Version=4.00

River Reach=NP1576          ,Main
Reach XY= 30
     1846762.419      214603.038     1846734.666      214583.241
     1846723.883      214569.007     1846692.519      214544.208
     1846636.357      214523.785     1846594.781       214506.28
     1846567.794      214509.927      1846548.13      214512.112
     1846541.536      214512.844     1846508.713      214509.198
     1846489.946      214500.536     1846463.491      214495.339
      1846429.21      214489.504     1846402.223      214486.587
     1846376.694      214471.999     1846345.331      214462.517
     1846319.802      214455.223     1846292.085      214443.552
     1846267.286      214438.447     1846215.499      214440.635
      1846167.36      214439.905     1846144.019      214445.011
     1846125.785      214448.658     1846099.527      214443.552
     1846060.139      214436.988     1846045.552      214426.777
     1846010.541      214419.483     1845980.492      214420.789
     1845908.885      214415.281     1845881.686      214417.815

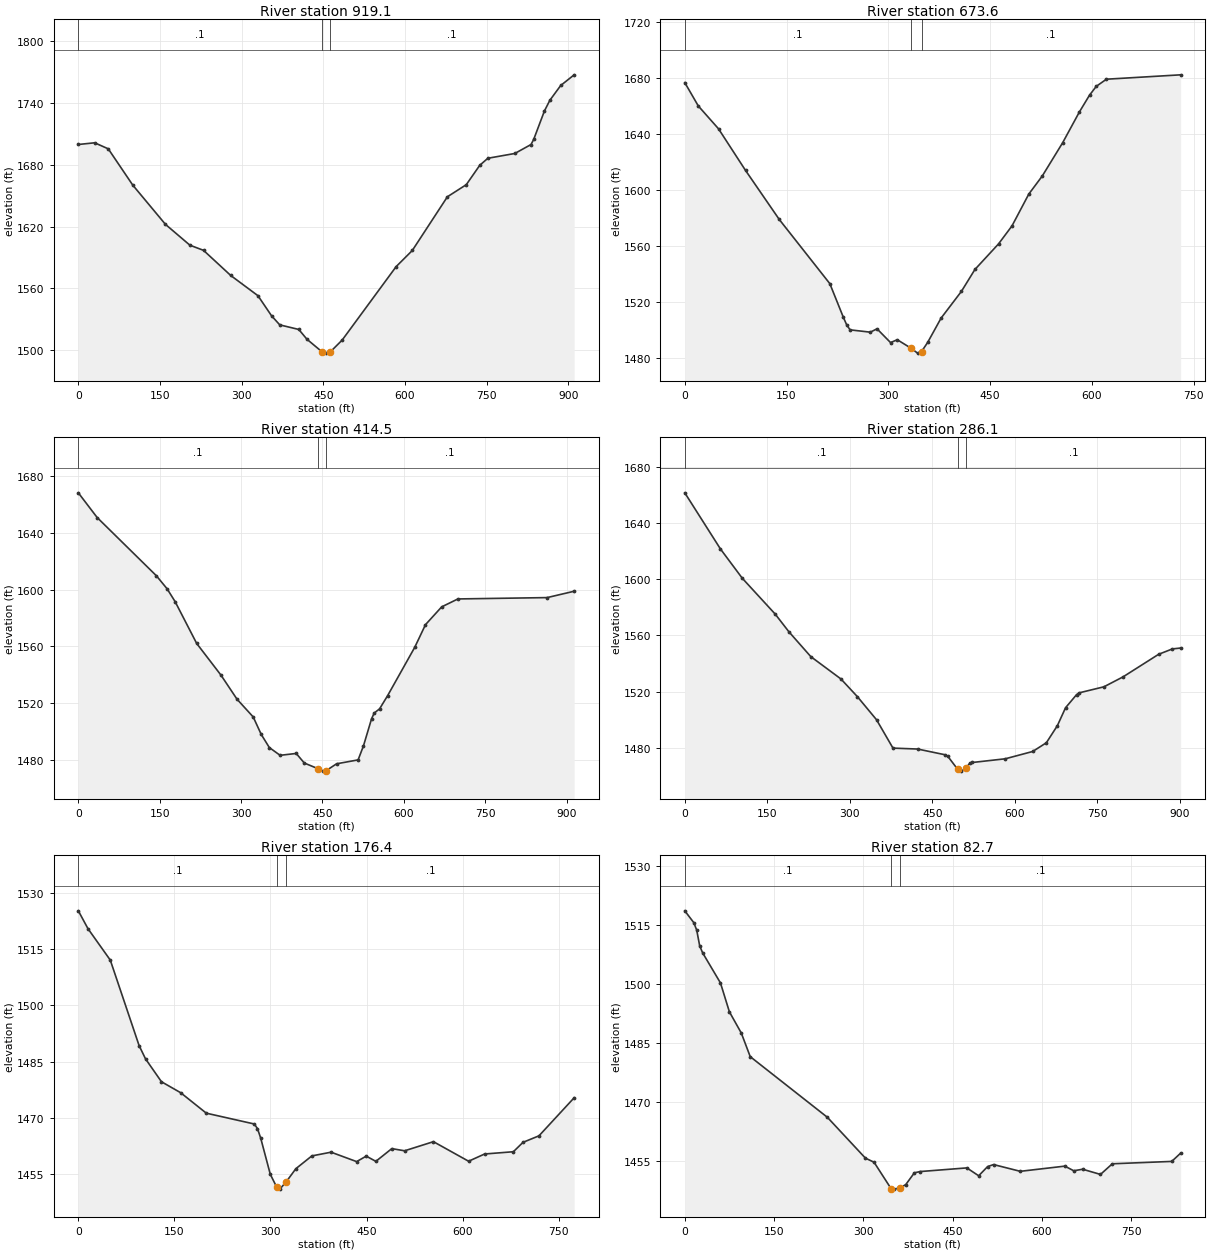
Type RM Length L Ch R = 1 ,919.1   ,252.3,245.5,239.7
XS GIS Cut Line= 3
      1847018.43      214226.928     1846754.278      214597.231
     1846509.581      214981.748
#Sta/Elev= 30
       0 1699.79      30 1701.45      55 1695.56     100 1660.27     160 1622.12
   204.9 1601.86   229.9 1596.86   279.9 1572.41   329.9 1552.73   354.9 1533.17
   369.9 1524.38   404.9 1519.91   419.9 1510.39   447.4 1498.24   454.9  1496.9
   462.4 1497.91   484.6 1509.63   583.7 1581.05   613.4 1596.76   677.8 1648.95
   712.5 1660.72   737.2 1679.54   752.1  1686.4   801.6 1691.05   831.4 1699.78
   836.3 1704.74   856.1 1732.52     866 1742.81   885.9 1757.17   910.6 1767.54
#Mann= 3 , 0 , 0
       0      .1       0   447.4    .045       0   462.4      .1       0
Bank Sta=447.4,462.4
XS Rating Curve= 0 ,0
Exp/Cntr=0.3,0.1

Type RM Length L Ch R = 1 ,673.6   ,266,259.1,252.1
XS GIS Cut Line= 2
     1846644.511      214188.333     1846413.345      214881.829
#Sta/Elev= 30
       0 1676.99    19.9 1660.32    49.7 1644.02    89.5 1614.32   139.2 1579.31
   213.8 1533.45   233.7 1509.47   238.7 1503.98   243.7 1500.44   273.5 1498.79
   283.4 1501.18   303.3 1491.37   313.3 1493.38     334 1487.19   343.1 1483.82
     349 1484.91     358 1491.42   377.9 1508.87   407.8  1527.9   427.7 1543.54
   462.5 1561.79   482.4 1574.69   507.2 1597.42   527.1 1610.36     557 1633.99
   581.8 1656.08   596.7 1668.03   606.7 1674.35   621.6 1679.42     731 1682.55
#Mann= 3 , 0 , 0
       0      .1       0     334    .045       0     349      .1       0
Bank Sta=334,349
XS Rating Curve= 0 ,0
Exp/Cntr=0.3,0.1

Type RM Length L Ch R = 1 ,414.5   ,129.5,128.4,127.5
XS GIS Cut Line= 3
     1846297.931      213993.651     1846286.994      214568.822
      1846233.26      214903.331
#Sta/Elev= 30
       0 1668.46    34.7 1651.01   143.8  1609.9   163.7 1600.63   178.5 1591.54
   218.2 1562.03   262.8 1539.73   292.6 1522.62   322.4  1510.1   337.2 1497.75
   352.1 1488.49     372 1482.99   401.7 1484.31   416.6 1477.53   441.9 1473.55
   451.3 1471.82   456.9 1472.16   476.1    1477   515.8 1479.76   525.7 1489.69
   540.6  1508.8   545.5 1512.87   555.4 1515.83   570.3 1525.22   620.1 1559.23
     640  1575.3   669.9 1587.89   699.8 1593.48   864.2 1594.43   914.1 1598.93
#Mann= 3 , 0 , 0
       0      .1       0   441.9    .045       0   456.9      .1       0
Bank Sta=441.9,456.9
XS Rating Curve= 0 ,0
Exp/Cntr=0.3,0.1

Type RM Length L Ch R = 1 ,286.1   ,112.1,109.7,108.2
XS GIS Cut Line= 2
     1846145.966      213937.625     1846174.044      214838.675
#Sta/Elev= 30
       0 1661.34    64.8 1621.45   104.6 1600.58   164.4 1575.13   189.3 1562.56
   229.1 1544.91   283.9 1529.02   313.8 1516.45   348.6 1500.04   378.5 1479.87
   423.4 1479.21   473.2 1475.14   478.1 1474.08   496.3 1464.73     503 1463.51
   511.3 1465.79     518 1469.02     523 1469.66   582.7 1472.28   632.5 1477.47
   657.4 1483.68   677.4 1495.82   692.3 1508.58   712.2 1517.82   717.2 1519.18
     762 1523.44   796.9 1530.53   861.6 1546.58   886.6 1550.39   901.5 1551.01
#Mann= 3 , 0 , 0
       0      .1       0   496.3    .045       0   511.3      .1       0
Bank Sta=496.3,511.3
XS Rating Curve= 0 ,0
Exp/Cntr=0.3,0.1

Type RM Length L Ch R = 1 ,176.4   ,91.5,93.7,95.1
XS GIS Cut Line= 2
     1846041.312      214116.304     1846074.495      214889.726
#Sta/Elev= 30
       0 1525.21      15 1520.47    49.9 1512.08    94.9  1489.3   104.9 1485.78
   129.8 1479.68   159.8 1476.76   199.8 1471.31   274.7 1468.43   279.7  1467.2
   284.7 1464.68   299.7 1455.03   309.8 1451.58   314.6 1451.08   324.8 1453.09
   339.6 1456.52   364.6 1459.93   394.6 1460.92   434.5 1458.41   449.5 1459.87
   464.5 1458.48   489.4 1461.87   509.4 1461.29   554.4 1463.72   609.3 1458.51
   634.3 1460.44   679.2 1461.04   694.2 1463.54   719.2 1465.28   774.1 1475.42
#Mann= 3 , 0 , 0
       0      .1       0   309.8    .045       0   324.8      .1       0
Bank Sta=309.8,324.8
XS Rating Curve= 0 ,0
Exp/Cntr=0.3,0.1

Type RM Length L Ch R = 1 ,82.7    ,83.9,82.7,81.4
XS GIS Cut Line= 5
     1846018.339      214098.436     1846025.996       214323.06
     1845962.183      214369.006     1845967.288      214504.291
     1846036.206      214892.278
#Sta/Elev= 30
       0 1518.57      15 1515.58      20 1513.68      25 1509.67      30 1507.87
    59.9 1500.23    74.9 1492.88    94.9 1487.48   109.9 1481.47   239.5 1466.04
   303.4 1455.65   317.9 1454.61   346.4 1447.91   351.7 1447.77   361.4 1448.09
   371.1 1448.92   385.6 1451.92   395.2 1452.24   473.7 1453.17   493.6 1451.17
   508.6  1453.5   518.6 1454.02   563.5  1452.3   638.3 1453.62   653.3 1452.44
   668.2 1452.83   698.2 1451.51   718.1 1454.22   817.9 1454.82   832.8 1456.92
#Mann= 3 , 0 , 0
       0      .1       0   346.4    .045       0   361.4      .1       0
Bank Sta=346.4,361.4
XS Rating Curve= 0 ,0
Exp/Cntr=0.3,0.1

Chan Stop Cuts=-1
Use User Specified Reach Order=0